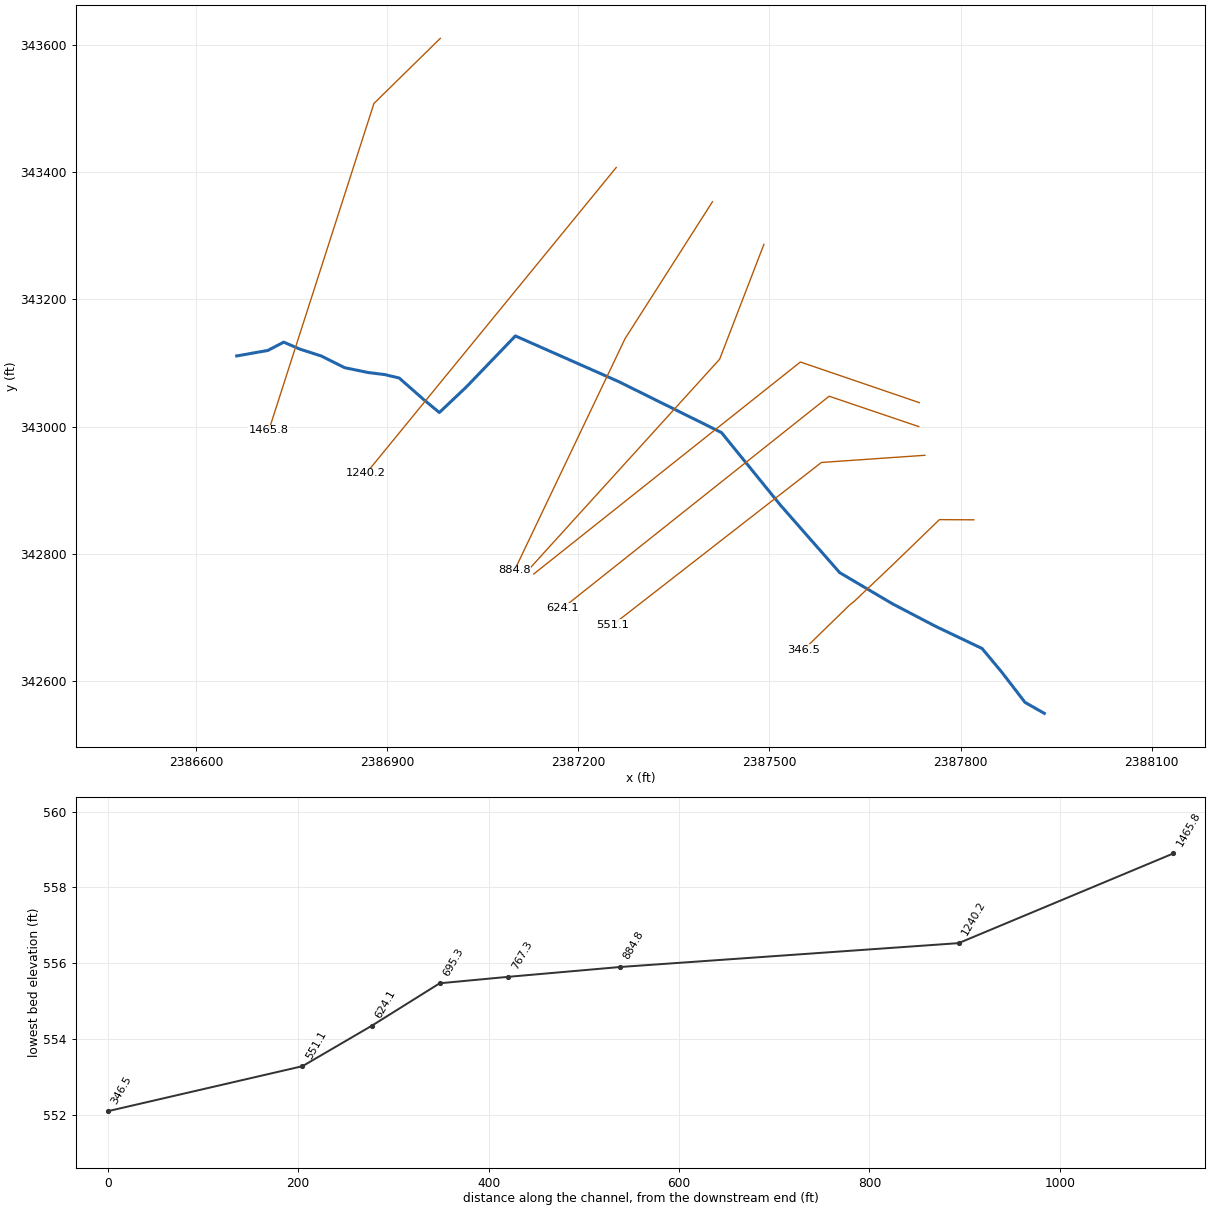
--- EVANSRUN.prj (project) ---

Proj Title=EVANSRUN
Current Plan=p01
Default Exp/Contr=0,0
English Units
Geom File=g01
Flow File=f01
Plan File=p01
BEGIN DESCRIPTION:
END DESCRIPTION:
DSS Export Rating Curves= 0
DSS Export Rating Curve Sorted= 0
DSS Export Volume Flow Curves= 0
DXF OffsetX= 0
DXF OffsetY= 0
DXF ScaleX= 0
DXF ScaleY= 0

--- EVANSRUN.p01 (plan) ---

Plan Title=Floodplain
Program Version=4.00
Geom File=g01
Flow File=f01
K Sum by GR=0
Std Step Tol=0.01
Critical Tol=0.01
Num of Std Step Trials=20
Max Error Tol=0.3
Flow Tol Ratio=0.001
Split Flow NTrial=30
Split Flow Tol=0.02
Split Flow Ratio=0.02
Log Output Level=0
Friction Slope Method=1
Unsteady Friction Slope Method=2
Unsteady Bridges Friction Slope Method=1
Global Log Level=0
CheckData=False
Run HTab=0
Run UNet=0
Run PostProcess=0
UNET Theta=0
UNET Theta Warmup=0
UNET ZTol=0
UNET ZSATol=0
UNET MxIter=0
UNET MaxInSteps=0
UNET DtIC=0
UNET DtMin=0
UNET MaxCRTS=0
UNET WFStab=0
UNET SFStab=0
UNET WFX=0
UNET SFX=0
UNET DSS MLevel=0
UNET DZMax Abort=0
UNET Convert EG Bridges=0
UNET Use Existing IB Tables=0
UNET Froude Limit=0
UNET Froude Power=0
Write IC File=0
Echo Input=False
Echo Output=False
Write Detailed=0

--- EVANSRUN.f01 (steady flow) ---

Flow Title=NFF Regression Equation
Program Version=5.03
Number of Profiles= 1
Profile Names=P100yr
River Rch & RM=EVANSRUN,Main            ,1465.8
533.0153
Boundary for River Rch & Prof#=EVANSRUN,Main            , 1
Up Type= 0
Dn Type= 1
Dn Known WS=555.4
DSS Import GetInterval= 0
DSS Import GetPeak= 0
DSS Import FillOption= 0

--- EVANSRUN.g01 (geometry) ---

Geom Title=USGS 10m DEM
Program Version=4.10

River Reach=EVANSRUN        ,Main
Reach XY= 23
     2386664.207       343111.19     2386713.035       343119.87
     2386737.991      343132.891     2386762.948      343122.041
     2386796.585       343111.19     2386833.478      343092.744
      2386870.37      343085.148     2386896.411      343081.893
     2386919.198      343076.468      2386956.09      343043.916
     2386982.132      343022.214      2387024.45      343062.362
      2387101.49      343142.657     2387263.165      343071.043
      2387424.84      342990.747     2387518.156       342875.73
     2387610.387      342770.478     2387692.852       342721.65
     2387761.212      342685.843     2387833.912       342651.12
     2387865.379      342613.143     2387901.186      342566.485
     2387931.568      342549.124

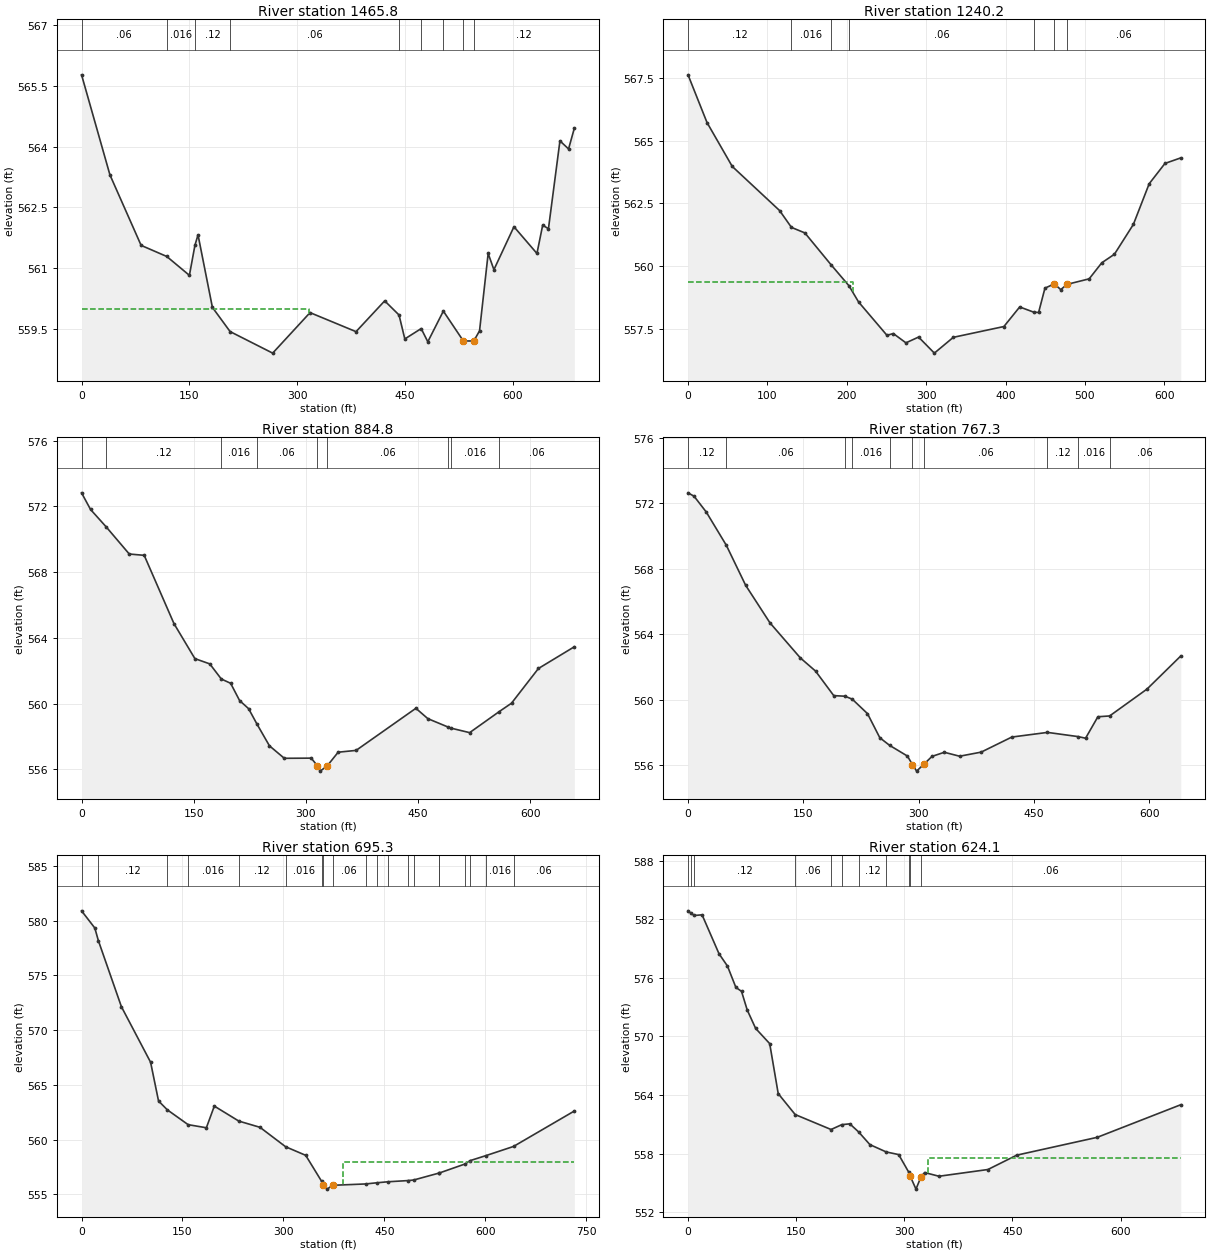
Type RM Length L Ch R = 1 ,1465.8  ,234.1,225.6,216.8
XS GIS Cut Line= 3
     2386983.679      343610.646     2386879.512      343508.216
     2386714.581      342994.327
#Sta/Elev= 30
       0  565.77    39.5   563.3    82.9  561.56  118.63561.2858   150.1  560.82
  157.81 561.563   162.1  561.82   182.1  560.03  206.74 559.432     266   558.9
     318   559.9     382  559.43   421.9  560.19  441.86559.8411   449.9  559.25
   472.7 559.506   481.9  559.18  503.53559.9371  531.39   559.2   545.9   559.2
   553.9  559.45   565.9  561.36   573.9  560.96   601.8  562.02   633.8  561.36
   641.8  562.06   649.8  561.97   665.8  564.14   677.8  563.94   685.8  564.45
#Mann= 9 ,-1 , 0
       0     .06       0  118.63    .016       0  157.81     .12       0
  206.74     .06       0  441.86    .016       0   472.7     .06       0
  503.53     .12       0  531.39    .045       0   545.9     .12       0
#XS Ineff= 2 , 0
          316.41     560
Permanent Ineff=
       F       F
Bank Sta=531.39,545.9
XS Rating Curve= 0 ,0
Exp/Cntr=0.3,0.1

Type RM Length L Ch R = 1 ,1240.2  ,344,355.4,360.3
XS GIS Cut Line= 2
      2387259.72      343407.521     2386867.359      342926.618
#Sta/Elev= 30
       0  567.62    23.9  565.72    55.7  563.97   115.4  562.21  130.26561.5412
   147.2  561.32  180.28560.0472  202.74559.2136   214.8  558.57   250.6  557.24
   258.6  557.31   274.5  556.94   290.4  557.17   310.3  556.53   334.2  557.16
   397.9  557.59   417.8  558.37  435.45558.1627   441.6  558.15   449.6  559.12
   461.5  559.29   469.5  559.06   477.4  559.27   505.3  559.49   521.2  560.13
   537.1  560.47     561  561.66   580.9  563.28   600.8  564.09   620.7  564.31
#Mann= 7 ,-1 , 0
       0     .12       0  130.26    .016       0  180.28     .12       0
  202.74     .06       0  435.45    .016       0   461.5    .045       0
   477.4     .06       0
#XS Ineff= 2 , 0
          207.33  559.36
Permanent Ineff=
       F       F
Bank Sta=461.5,477.4
XS Rating Curve= 0 ,0
Exp/Cntr=0.3,0.1

Type RM Length L Ch R = 1 ,884.8   ,124.2,117.5,110.8
XS GIS Cut Line= 3
     2387410.762      343353.702     2387273.609      343138.424
     2387099.998      342773.841
#Sta/Elev= 30
       0  572.82      12  571.81   33.12570.7398    63.8   569.1    83.8  569.02
   123.6  564.87   151.6  562.74   171.5  562.42  186.93561.5016   199.4  561.24
   211.4  560.19   223.4   559.7  234.79558.7472   251.3  557.44   271.2  556.68
   307.2  556.69   315.2  556.24   319.2   555.9   328.6  556.22   343.2  557.05
   367.2  557.16   447.2  559.72   463.2  559.09  490.15558.5819  494.33558.5115
   519.1  558.24  558.71559.5205   575.1  560.03   611.1  562.14   659.1  563.46
#Mann= 9 ,-1 , 0
       0     .06       0   33.12     .12       0  186.93    .016       0
  234.79     .06       0   315.2    .045       0   328.6     .06       0
  490.15     .12       0  494.33    .016       0  558.71     .06       0
Bank Sta=315.2,328.6
XS Rating Curve= 0 ,0
Exp/Cntr=0.3,0.1

Type RM Length L Ch R = 1 ,767.3   ,76.2,72,67.9
XS GIS Cut Line= 3
      2387491.44      343286.568     2387421.996      343106.012
     2387121.648      342774.415
#Sta/Elev= 30
       0  572.63     7.9  572.42    23.7  571.46   49.77569.4316      75  566.98
   106.6  564.69   146.1  562.55   165.8  561.75   189.5  560.25  204.06560.2134
  213.57560.0336   233.4  559.15   249.4  557.68  262.04557.2172   285.3  556.56
   291.9  556.04   297.3  555.64   306.9  556.07   317.3  556.54   333.3  556.79
   353.2  556.55   381.2   556.8   421.1  557.72  467.47558.0041  507.01557.7498
     517  557.65     533  558.96  548.27559.0082   596.9  560.65   640.8  562.67
#Mann= 10 ,-1 , 0
       0     .12       0   49.77     .06       0  204.06     .12       0
  213.57    .016       0  262.04     .06       0   291.9    .045       0
   306.9     .06       0  467.47     .12       0  507.01    .016       0
  548.27     .06       0
Bank Sta=291.9,306.9
XS Rating Curve= 0 ,0
Exp/Cntr=0.3,0.1

Type RM Length L Ch R = 1 ,695.3   ,70.7,71.2,71.7
XS GIS Cut Line= 3
     2387735.415       343037.73     2387548.732      343101.672
     2387130.329      342768.339
#Sta/Elev= 30
       0  580.91    19.7  579.34   24.97578.1874    59.2  572.15   102.6  567.07
   114.4  563.53  127.38562.7228   158.4561.3628   185.5  561.08   197.3  563.06
  233.72561.6896   265.2  561.12   303.3 559.343   333.1  558.56  356.81556.1799
  358.68  555.88     365  555.47     373  555.82  422.25555.9435  438.39556.0476
  455.31556.1423  484.79556.2499  493.55556.3034   531.2556.9375   531.8556.9465
  570.04557.7712  577.61558.0779  600.82558.5308  641.94559.3706   732.3  562.61
#Mann= 20 ,-1 , 0
       0     .06       0   24.97     .12       0  127.38     .06       0
   158.4    .016       0  233.72     .12       0   303.3    .016       0
  356.81     .06       0  358.68    .045       0     373     .06       0
  422.25     .12       0  438.39     .06       0  455.31     .12       0
  484.79    .016       0  493.55     .06       0   531.2    .016       0
   531.8     .06       0  570.04     .12       0  577.61     .06       0
  600.82    .016       0  641.94     .06       0
#XS Ineff= 2 , 0
                          388.85          557.99
Permanent Ineff=
       F       F
Bank Sta=358.68,373
XS Rating Curve= 0 ,0
Exp/Cntr=0.3,0.1

Type RM Length L Ch R = 1 ,624.1   ,73.2,72.9,72.7
XS GIS Cut Line= 3
     2387734.496       343000.11     2387593.871      343047.853
     2387175.468      342714.519
#Sta/Elev= 30
       0  582.87    3.86582.6324    8.68582.3942    19.5  582.46      43  578.47
    54.7  577.21    66.4  575.02    74.2  574.62    82.1  572.71    93.8  570.82
   113.3  569.26   125.1  564.14  148.64561.9927  198.41  560.46  213.32560.9576
   224.4  561.04  236.65560.2111   252.3  558.91   274.9558.1615   292.2  557.89
  306.13556.0888   308.3  555.66   316.2  554.35   323.3  555.64   328.2  556.05
   348.1  555.67     416  556.36   455.9  557.83   567.7  559.66   683.5     563
#Mann= 11 ,-1 , 0
       0     .12       0    3.86     .06       0    8.68     .12       0
  148.64     .06       0  198.41     .12       0  213.32     .08       0
  236.65     .12       0   274.9     .08       0  306.13     .06       0
   308.3    .045       0   323.3     .06       0
#XS Ineff= 2 , 0
                           332.3          557.51
Permanent Ineff=
       F       F
Bank Sta=308.3,323.3
XS Rating Curve= 0 ,0
Exp/Cntr=0.3,0.1

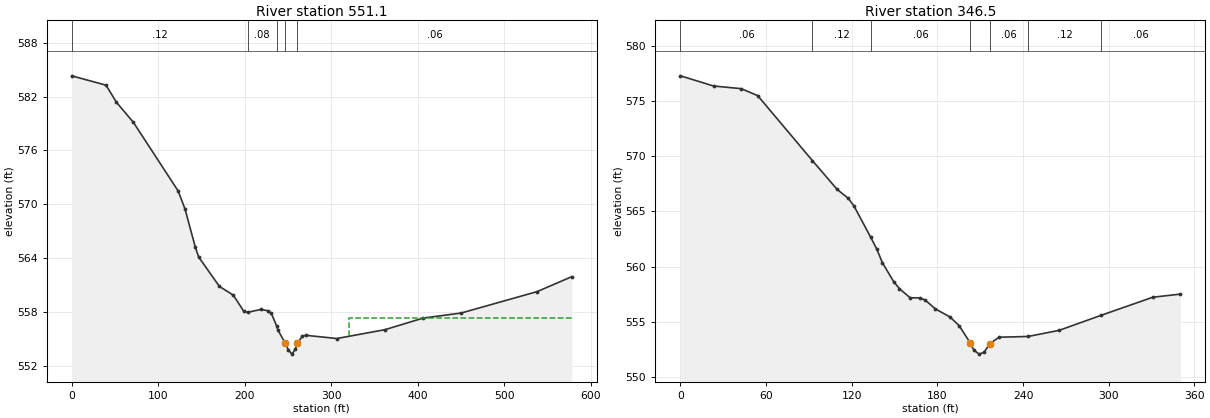
Type RM Length L Ch R = 1 ,551.1   ,202.3,204.6,206.9
XS GIS Cut Line= 3
     2387744.044      342954.971     2387581.718      342943.686
     2387254.461      342688.478
#Sta/Elev= 30
       0  584.31    39.7  583.27    51.6  581.38    71.4  579.11     123  571.48
     131  569.45   142.9  565.19   146.8   564.1   170.7  560.83   186.7  559.86
   198.6   558.1  203.18557.9371   218.6  558.26   226.6  558.12   230.6  557.85
  236.73556.4474   238.5  555.93   246.5  554.56   250.5  553.74   254.5  553.28
   258.5  553.85  260.89   554.5   266.5  555.27   270.5  555.38   306.4  555.02
   362.2  556.01   406.1   557.3     450  557.86   537.8  560.25   577.7  561.91
#Mann= 5 ,-1 , 0
       0     .12       0  203.18     .08       0  236.73     .06       0
   246.5    .045       0  260.89     .06       0
#XS Ineff= 2 , 0
                          320.12          557.33
Permanent Ineff=
       F       F
Bank Sta=246.5,260.89
XS Rating Curve= 0 ,0
Exp/Cntr=0.3,0.1

Type RM Length L Ch R = 1 ,346.5   ,340,346.5,352.9
XS GIS Cut Line= 6
     2387820.951      342853.493      2387766.89      342853.787
     2387692.755       342781.91     2387633.681       342725.73
     2387625.224      342718.811     2387553.405       342648.68
#Sta/Elev= 30
       0  577.27    23.2  576.35    42.5  576.11    54.1  575.48    92.4569.6045
   109.7     567   117.6  566.18   121.6  565.48  133.22 562.673   137.5   561.6
   141.4  560.37   149.4  558.64   153.4  558.01   160.9  557.19     168  557.18
   171.6  556.96   178.6  556.18   188.7  555.46   195.2  554.67     203   553.1
   205.6  552.44   209.2  552.09   212.7  552.26  216.82  553.05   223.2  553.62
  243.51553.6872   265.2  554.24  294.54 555.596   330.9  557.24   350.2  557.52
#Mann= 7 ,-1 , 0
       0     .06       0    92.4     .12       0  133.22     .06       0
     203    .045       0  216.82     .06       0  243.51     .12       0
  294.54     .06       0
Bank Sta=203,216.82
XS Rating Curve= 0 ,0
Exp/Cntr=0.3,0.1

Chan Stop Cuts=-1
Use User Specified Reach Order=0
Composite Channel Slope=5